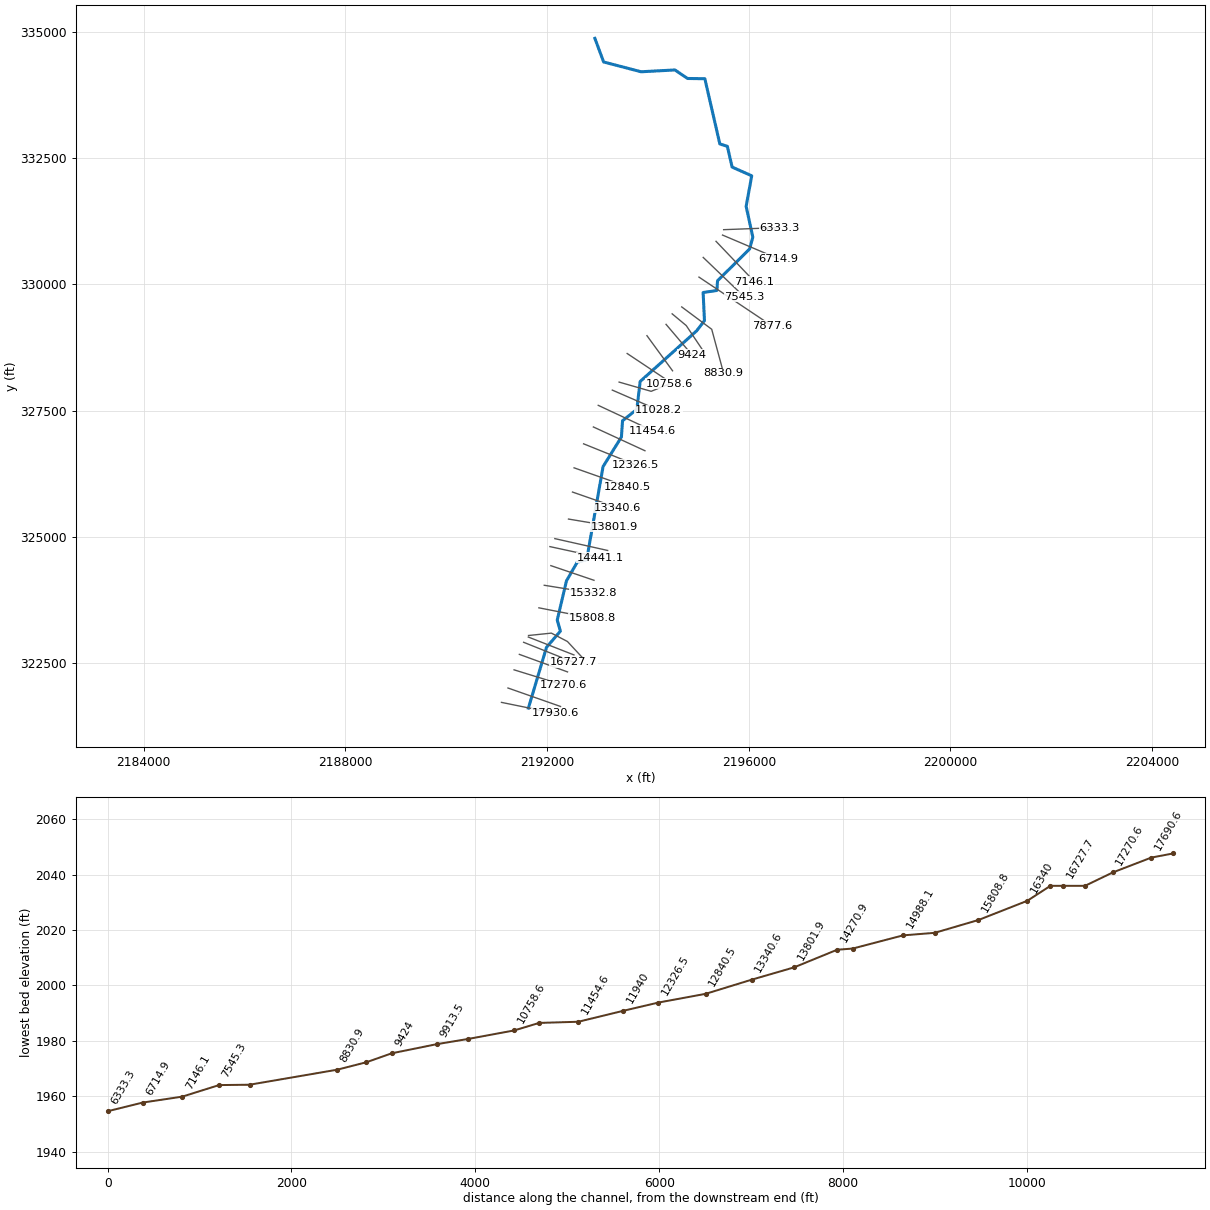
--- FlemRun.prj (project) ---

Proj Title=FlemRun
Current Plan=p01
Default Exp/Contr=0,0
English Units
Geom File=g01
Flow File=f01
Plan File=p01
BEGIN DESCRIPTION:
END DESCRIPTION:
DSS Export Rating Curves= 0
DSS Export Rating Curve Sorted= 0
DSS Export Volume Flow Curves= 0
DXF OffsetX= 0
DXF OffsetY= 0
DXF ScaleX= 0
DXF ScaleY= 0

--- FlemRun.p01 (plan) ---

Plan Title=Floodplain
Program Version=4.00
Geom File=g01
Flow File=f01
K Sum by GR=0
Std Step Tol=0.01
Critical Tol=0.01
Num of Std Step Trials=20
Max Error Tol=0.3
Flow Tol Ratio=0.001
Split Flow NTrial=30
Split Flow Tol=0.02
Split Flow Ratio=0.02
Log Output Level=0
Friction Slope Method=1
Unsteady Friction Slope Method=2
Unsteady Bridges Friction Slope Method=1
Global Log Level=0
CheckData=False
Run HTab=0
Run UNet=0
Run PostProcess=0
UNET Theta=0
UNET Theta Warmup=0
UNET ZTol=0
UNET ZSATol=0
UNET MxIter=0
UNET MaxInSteps=0
UNET DtIC=0
UNET DtMin=0
UNET MaxCRTS=0
UNET WFStab=0
UNET SFStab=0
UNET WFX=0
UNET SFX=0
UNET DSS MLevel=0
UNET DZMax Abort=0
UNET Convert EG Bridges=0
UNET Use Existing IB Tables=0
UNET Froude Limit=0
UNET Froude Power=0
Write IC File=0
Echo Input=False
Echo Output=False
Write Detailed=0

--- FlemRun.f01 (steady flow) ---

Flow Title=NFF Regression Equation
Program Version=4.00
Number of Profiles=1
Profile Names=P100yr
River Rch & RM=FlemRun,Main      ,17930.6
515.0376
River Rch & RM=FlemRun,Main      ,17270.6
610.2454
River Rch & RM=FlemRun,Main      ,16340
635.9109
River Rch & RM=FlemRun,Main      ,15808.8
801.7101
River Rch & RM=FlemRun,Main      ,14441.1
838.5739
River Rch & RM=FlemRun,Main      ,12840.5
914.7124
River Rch & RM=FlemRun,Main      ,9424
1005.094
River Rch & RM=FlemRun,Main      ,9149.4
1170.013
River Rch & RM=FlemRun,Main      ,7877.6
1175.070
River Rch & RM=FlemRun,Main      ,7545.3
1636.177
River Rch & RM=FlemRun,Main      ,2791.7
1708.672
Boundary for River Rch & Prof#=FlemRun,Main      ,1
Up Type=0
Dn Type=3
Dn Slope=0.006502

--- FlemRun.g01 (geometry) ---

Geom Title=USGS 10m DEM
Program Version=4.10

River Reach=FlemRun         ,Main
Reach XY= 30
     2191628.359       321615.96     2191986.607      322816.809
     2192262.734      323139.397     2192200.235      323358.147
     2192383.047      324131.584     2192597.109      324503.459
      2192784.08      324552.203     2193109.609      326394.084
     2193473.672      326980.022     2193495.547      327300.335
     2193778.657      327526.469     2193845.547      328078.459
      2194965.86      329080.022     2195120.547      329281.585
     2195093.985      329837.834     2195367.422      329878.459
     2195379.922      330070.647      2196015.86      330698.772
     2196079.922      330933.147      2195947.11      331542.522
     2196058.047      332147.209     2195668.985      332319.084
     2195574.142      332730.147     2195425.235      332776.897
      2195128.36      334067.522      2194784.61       334072.21
      2194534.61       334240.96     2193864.297      334205.022
     2193120.547      334398.772     2192946.732      334866.383

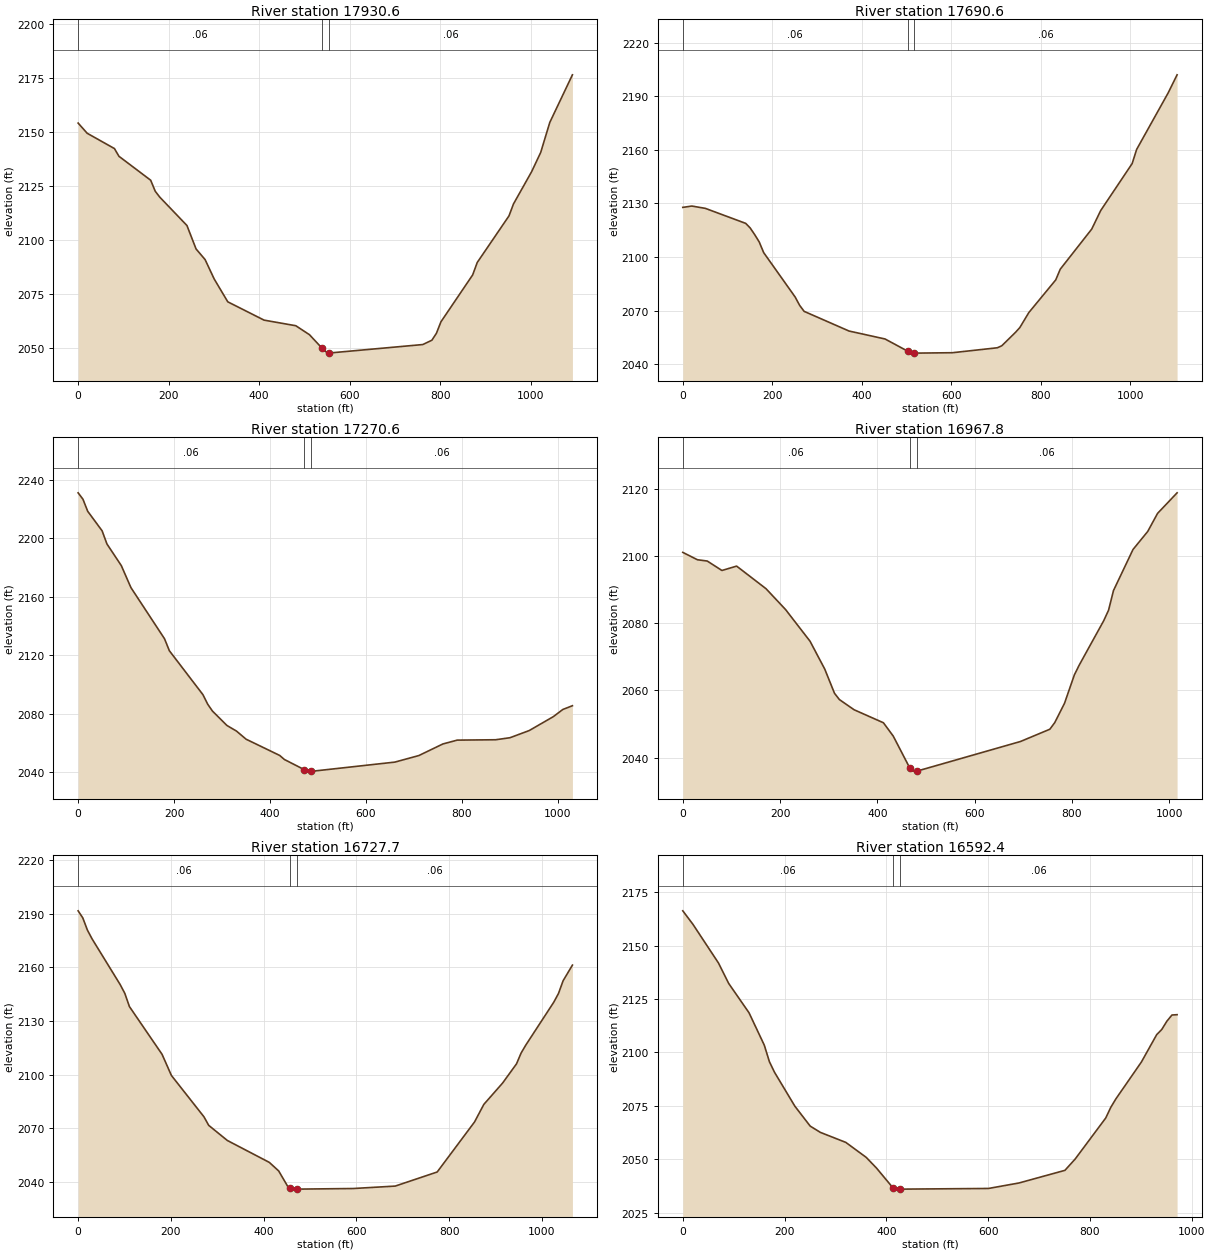
Type RM Length L Ch R = 1 ,17930.6 ,243.1,240,237
XS GIS Cut Line= 2
     2191094.169      321729.234     2192164.343      321511.734
#Sta/Elev= 30
       0 2154.16      20 2149.44    80.2 2142.36    90.2 2138.78   160.3  2127.7
   170.3 2122.62   180.3 2119.89   240.4 2106.74   260.5  2095.9   280.5 2090.97
   300.6 2081.99   330.6 2071.42   410.8 2062.94   480.9 2060.35     511 2056.21
   538.5 2050.04     551 2047.67   553.5  2047.7   761.4 2051.64   781.5 2053.64
   791.5 2056.84   801.5 2062.16   871.6 2083.87   881.7 2089.62   951.8 2111.18
   961.8 2116.73  1001.9 2131.68  1021.9 2140.56    1042 2154.46    1092 2176.49
#Mann= 3 , 0 , 0
       0     .06       0   538.5    .045       0   553.5     .06       0
Bank Sta=538.5,553.5
XS Rating Curve= 0 ,0
Exp/Cntr=0.3,0.1

Type RM Length L Ch R = 1 ,17690.6 ,418.5,419.7,420.9
XS GIS Cut Line= 2
      2191223.08      322013.556     2192265.693      321648.466
#Sta/Elev= 30
       0 2127.79    20.1 2128.54    50.2 2127.26   140.6 2118.84   150.6 2116.28
   160.7 2112.53   170.7 2108.49   180.8 2102.45   251.1 2077.61   261.1 2072.95
   271.2 2069.56   371.6 2058.54   451.9  2054.1   502.8 2047.25   512.2 2046.17
   517.8 2046.17   602.6  2046.4     703 2049.17     713  2050.3   743.2 2057.72
   753.2 2060.47   773.3 2068.86   833.5 2087.18   843.6 2093.18   913.9 2115.63
     934 2126.03  1004.3 2152.34  1014.3 2160.25  1084.6 2191.84  1104.7 2202.03
#Mann= 3 , 0 , 0
       0     .06       0   502.8    .045       0   517.8     .06       0
Bank Sta=502.8,517.8
XS Rating Curve= 0 ,0
Exp/Cntr=0.3,0.1

Type RM Length L Ch R = 1 ,17270.6 ,303.9,302.9,301.8
XS GIS Cut Line= 2
     2191344.192      322372.941     2192328.882      322069.723
#Sta/Elev= 30
       0 2231.08      10 2226.73      20 2218.45      50  2205.1      60 2196.15
      90 2181.32     110 2166.31   180.1 2131.29   190.1 2123.15   260.1  2093.1
   270.1 2086.55   280.1 2081.82   310.1 2072.03   330.1 2068.17   350.1 2062.63
   420.1 2051.53   430.1 2048.72   471.2 2041.85   486.2 2040.86   490.2  2040.8
   660.2 2046.97   710.2 2051.45   760.2 2059.36   790.2    2062   870.3 2062.25
   900.3 2063.65   940.3 2068.55   990.3 2078.01  1010.3 2082.96  1030.3 2085.52
#Mann= 3 , 0 , 0
       0     .06       0   471.2    .045       0   486.2     .06       0
Bank Sta=471.2,486.2
XS Rating Curve= 0 ,0
Exp/Cntr=0.3,0.1

Type RM Length L Ch R = 1 ,16967.8 ,240.8,240.1,239.3
XS GIS Cut Line= 2
      2191449.06      322678.893     2192404.546      322331.978
#Sta/Elev= 30
       0 2101.09    30.2 2098.89    50.3 2098.51    80.5  2095.7   110.7    2097
   171.1 2090.28   211.4 2084.06   261.7 2074.63   291.9 2066.35     312 2059.13
   322.1 2057.26   352.3 2054.23   412.6 2050.36   432.8 2046.39   466.7 2036.92
     473 2035.96   481.7 2035.97   694.4 2044.78   754.8 2048.43   764.9  2050.4
     785 2056.16   805.2  2064.6   815.2 2067.52   865.6 2080.74   875.6 2083.88
   885.7 2089.72   925.9 2101.96   956.1 2107.31   976.3 2112.69  1016.5 2118.82
#Mann= 3 , 0 , 0
       0     .06       0   466.7    .045       0   481.7     .06       0
Bank Sta=466.7,481.7
XS Rating Curve= 0 ,0
Exp/Cntr=0.3,0.1

Type RM Length L Ch R = 1 ,16727.7 ,134.8,135.4,136
XS GIS Cut Line= 2
     2191533.758      322917.943     2192523.713      322523.014
#Sta/Elev= 30
       0 2191.62      10  2187.7    20.1  2180.8    30.2 2175.88    90.5 2150.44
   100.6  2145.5   110.6 2138.07     181 2111.36   201.1 2099.56   271.5 2076.35
   281.5 2071.65   321.8 2063.17   412.2 2050.93   432.4 2046.16   452.5 2037.23
   456.8 2036.71   471.8 2035.97   593.2 2036.31   683.7 2037.67   774.2 2045.55
   854.7 2073.52   874.8 2083.37     915 2095.22   945.2 2106.02   955.2 2112.11
   965.3 2116.55  1025.6 2140.52  1035.7 2145.38  1045.7 2152.51  1065.8 2161.26
#Mann= 3 , 0 , 0
       0     .06       0   456.8    .045       0   471.8     .06       0
Bank Sta=456.8,471.8
XS Rating Curve= 0 ,0
Exp/Cntr=0.3,0.1

Type RM Length L Ch R = 1 ,16592.4 ,255,252.1,249.3
XS GIS Cut Line= 2
     2191627.111      323021.673     2192531.699      322667.776
#Sta/Elev= 30
       0 2166.35      20 2160.01    70.1 2141.92    90.1 2132.37   130.2 2118.58
   160.2  2103.4   170.2 2095.68   180.2 2090.74   220.3 2074.81   250.4 2065.49
   270.4 2062.55   320.4 2057.86   360.5 2050.84   380.5 2045.88   412.7 2036.67
   427.7 2035.98   430.6 2035.97   600.8 2036.28   660.9 2038.86     751 2044.77
   771.1 2050.07   831.2  2069.3   841.2 2074.34   851.2 2078.28   901.2  2095.5
   931.3 2108.34   941.3 2110.77   951.3 2114.63   961.3 2117.54   971.4 2117.69
#Mann= 3 , 0 , 0
       0     .06       0   412.7    .045       0   427.7     .06       0
Bank Sta=412.7,427.7
XS Rating Curve= 0 ,0
Exp/Cntr=0.3,0.1

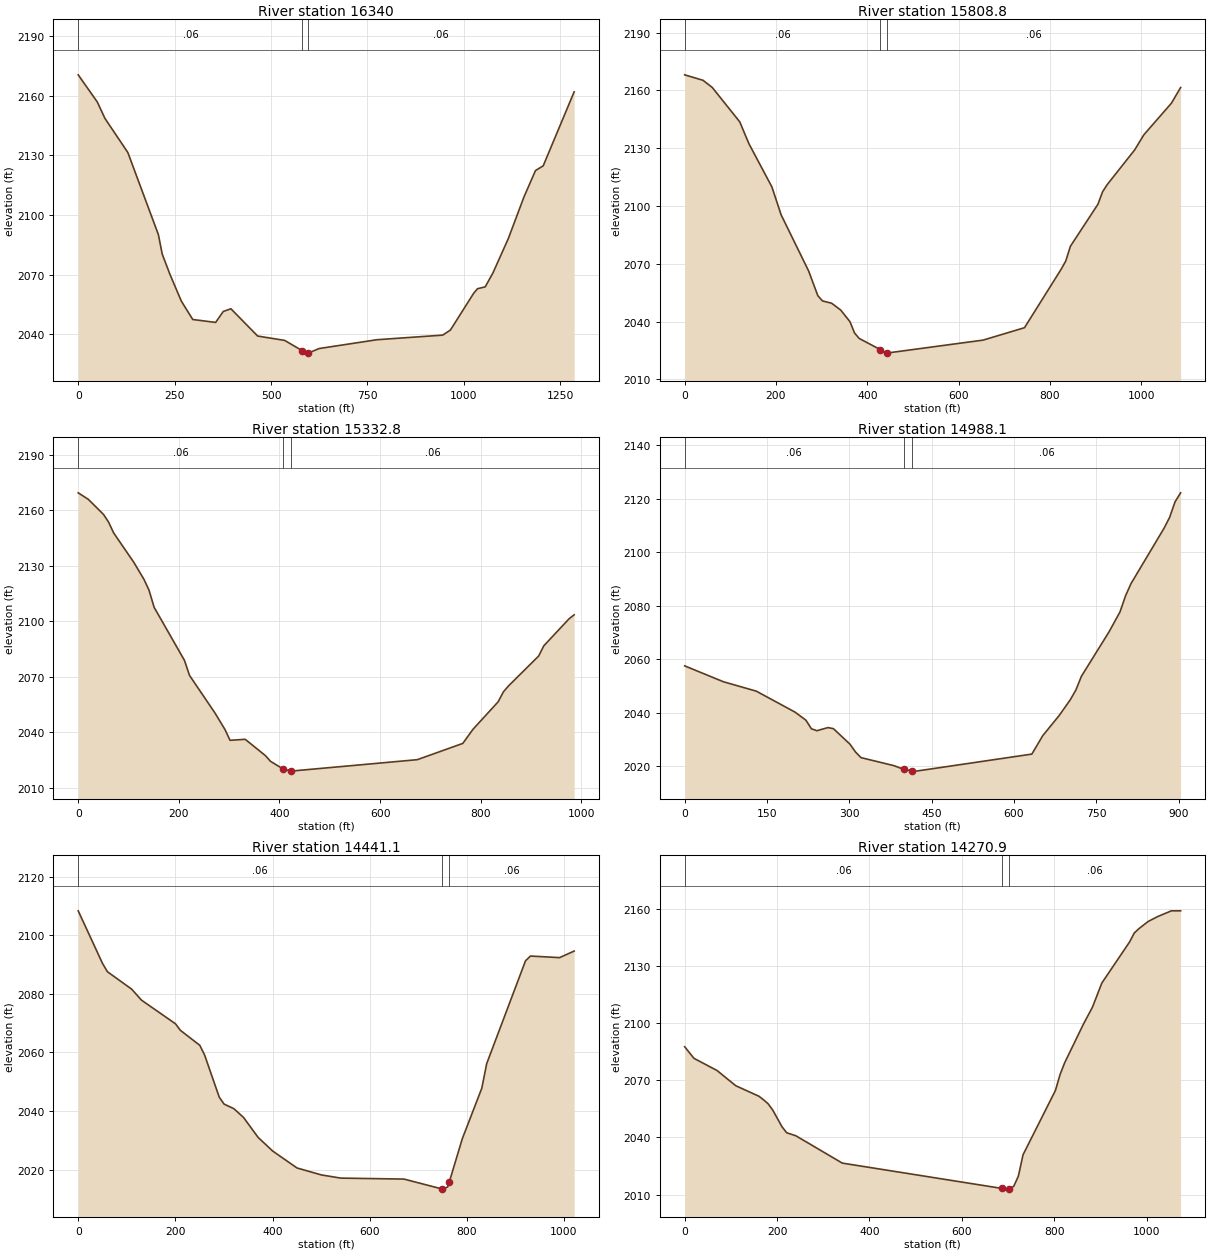
Type RM Length L Ch R = 1 ,16340   ,525.2,531.1,537.1
XS GIS Cut Line= 4
     2191631.174      323052.219     2192084.026       323099.61
     2192402.602       322933.74     2192723.811      322588.836
#Sta/Elev= 30
       0 2170.47    49.5 2156.81    69.3 2148.57   128.7 2131.41   207.9 2090.12
   217.8 2080.36   237.6 2070.29   267.3 2056.73     297 2047.46   356.3    2046
   376.1  2051.5   395.9 2052.86   465.3 2039.14   535.1 2036.97   581.3 2031.74
     595 2030.56   596.3 2030.57   624.9 2032.88   774.6  2037.3   944.9 2039.61
   964.9 2042.13  1025.1  2060.6  1035.1 2062.93  1055.2 2063.88  1075.2 2070.86
  1115.3 2088.23  1155.4 2108.94  1185.5 2122.33  1205.6 2124.73  1285.8 2161.92
#Mann= 3 , 0 , 0
       0     .06       0   581.3    .045       0   596.3     .06       0
Bank Sta=581.3,596.3
XS Rating Curve= 0 ,0
Exp/Cntr=0.3,0.1

Type RM Length L Ch R = 1 ,15808.8 ,475.1,476,476.9
XS GIS Cut Line= 2
     2191836.537      323599.854     2192902.845      323391.858
#Sta/Elev= 30
       0 2168.12    40.2 2165.28    60.4 2161.56   120.7 2143.69   140.8 2132.33
   191.1  2109.9   211.2 2095.48   271.6 2066.25   291.7 2053.45   301.8 2050.75
   321.9 2049.54     342 2045.95   362.1 2039.94   372.2 2034.07   382.2 2031.27
   428.7 2025.44   442.6 2023.63   443.7 2023.69   653.8 2030.39   744.4 2036.83
   824.9 2067.26   834.9 2071.52     845 2079.12   905.3 2100.93   915.4 2107.38
   925.5 2111.09   985.8 2129.16  1005.9    2137  1066.3 2153.41  1086.4 2161.53
#Mann= 3 , 0 , 0
       0     .06       0   428.7    .045       0   443.7     .06       0
Bank Sta=428.7,443.7
XS Rating Curve= 0 ,0
Exp/Cntr=0.3,0.1

Type RM Length L Ch R = 1 ,15332.8 ,348.4,344.6,340.8
XS GIS Cut Line= 2
     2191942.729      324046.124      2192916.01      323889.469
#Sta/Elev= 30
       0 2169.52    20.1    2166    50.3 2157.84    60.4 2153.66    70.4 2147.86
   110.6  2131.9   130.8 2122.68   140.8 2116.84   150.9  2107.6   211.2  2078.9
   221.3 2070.75   271.6 2050.55   291.7 2041.52   301.8 2035.67     332  2036.2
   372.2 2027.37   382.2 2024.32   407.6  2020.1   422.5    2019   422.6    2019
     674 2025.19   764.5    2034   784.6 2041.59   834.9 2056.55     845 2061.82
     855 2064.99   915.4  2081.3   925.4 2086.75   975.8 2101.43   985.8 2103.54
#Mann= 3 , 0 , 0
       0     .06       0   407.6    .045       0   422.6     .06       0
Bank Sta=407.6,422.6
XS Rating Curve= 0 ,0
Exp/Cntr=0.3,0.1

Type RM Length L Ch R = 1 ,14988.1 ,542.7,547,551.2
XS GIS Cut Line= 2
     2192073.494      324434.471     2192929.174      324144.856
#Sta/Elev= 30
       0 2057.46    70.3 2051.53   130.5 2047.99   200.8 2040.18   220.8 2037.14
   230.9 2033.91   240.9  2033.2     261 2034.37     271 2033.96   301.1 2028.16
   311.2 2025.23   321.2 2023.13   381.4 2020.12   399.1 2018.74   414.1 2018.14
   421.6 2018.08   632.4 2024.45   652.4 2031.38   682.5 2038.96   702.6 2044.84
   712.6 2048.41   722.7 2053.56   772.9 2070.14     793 2077.65     803 2083.62
     813 2088.21   873.2 2108.93   883.3 2112.97   893.3 2118.83   903.4 2122.18
#Mann= 3 , 0 , 0
       0     .06       0   399.1    .045       0   414.1     .06       0
Bank Sta=399.1,414.1
XS Rating Curve= 0 ,0
Exp/Cntr=0.3,0.1

Type RM Length L Ch R = 1 ,14441.1 ,170.3,170.2,170
XS GIS Cut Line= 2
     2192055.064       324810.97     2193052.918      324595.075
#Sta/Elev= 30
       0  2108.3      50 2090.36    60.1 2087.53   110.1 2081.56   130.1 2077.84
   200.2 2069.76   210.2 2067.54   250.2 2062.42   260.2  2059.1   290.3 2044.73
   300.3 2042.34   320.3  2040.8   340.3  2037.8   370.3 2030.99   400.4 2026.32
   450.4 2020.55   500.5 2018.18   540.5 2017.09   670.6 2016.76   748.6  2013.4
   750.7 2013.33   760.7 2014.09   763.6 2015.62   790.7 2030.55   830.8 2047.77
   840.8 2056.12   920.8 2091.25   930.9 2092.87   990.9 2092.33  1020.9 2094.57
#Mann= 3 , 0 , 0
       0     .06       0   748.6    .045       0   763.6     .06       0
Bank Sta=748.6,763.6
XS Rating Curve= 0 ,0
Exp/Cntr=0.3,0.1

Type RM Length L Ch R = 1 ,14270.9 ,467.5,469,470.4
XS GIS Cut Line= 2
      2192152.48      324968.941     2193200.359      324734.617
#Sta/Elev= 30
       0 2087.61    20.1 2081.53    70.2 2075.12   110.4 2067.18   160.6 2061.65
   170.6 2059.81   180.6  2057.7   190.7 2054.37   210.7 2045.63   220.8 2042.48
   240.8 2040.88   341.2 2026.55   687.2 2013.25   702.2 2012.89   712.5 2014.37
   722.5 2019.68   732.6 2030.91   802.8  2064.7   812.8 2073.04   822.9 2079.28
     863 2099.29   883.1 2108.47   903.2 2121.03   963.4 2142.63   973.4 2147.27
   983.4 2149.56  1003.5 2153.33  1023.6 2155.86  1053.7 2158.92  1073.8 2158.93
#Mann= 3 , 0 , 0
       0     .06       0   687.2    .045       0   702.2     .06       0
Bank Sta=687.2,702.2
XS Rating Curve= 0 ,0
Exp/Cntr=0.3,0.1

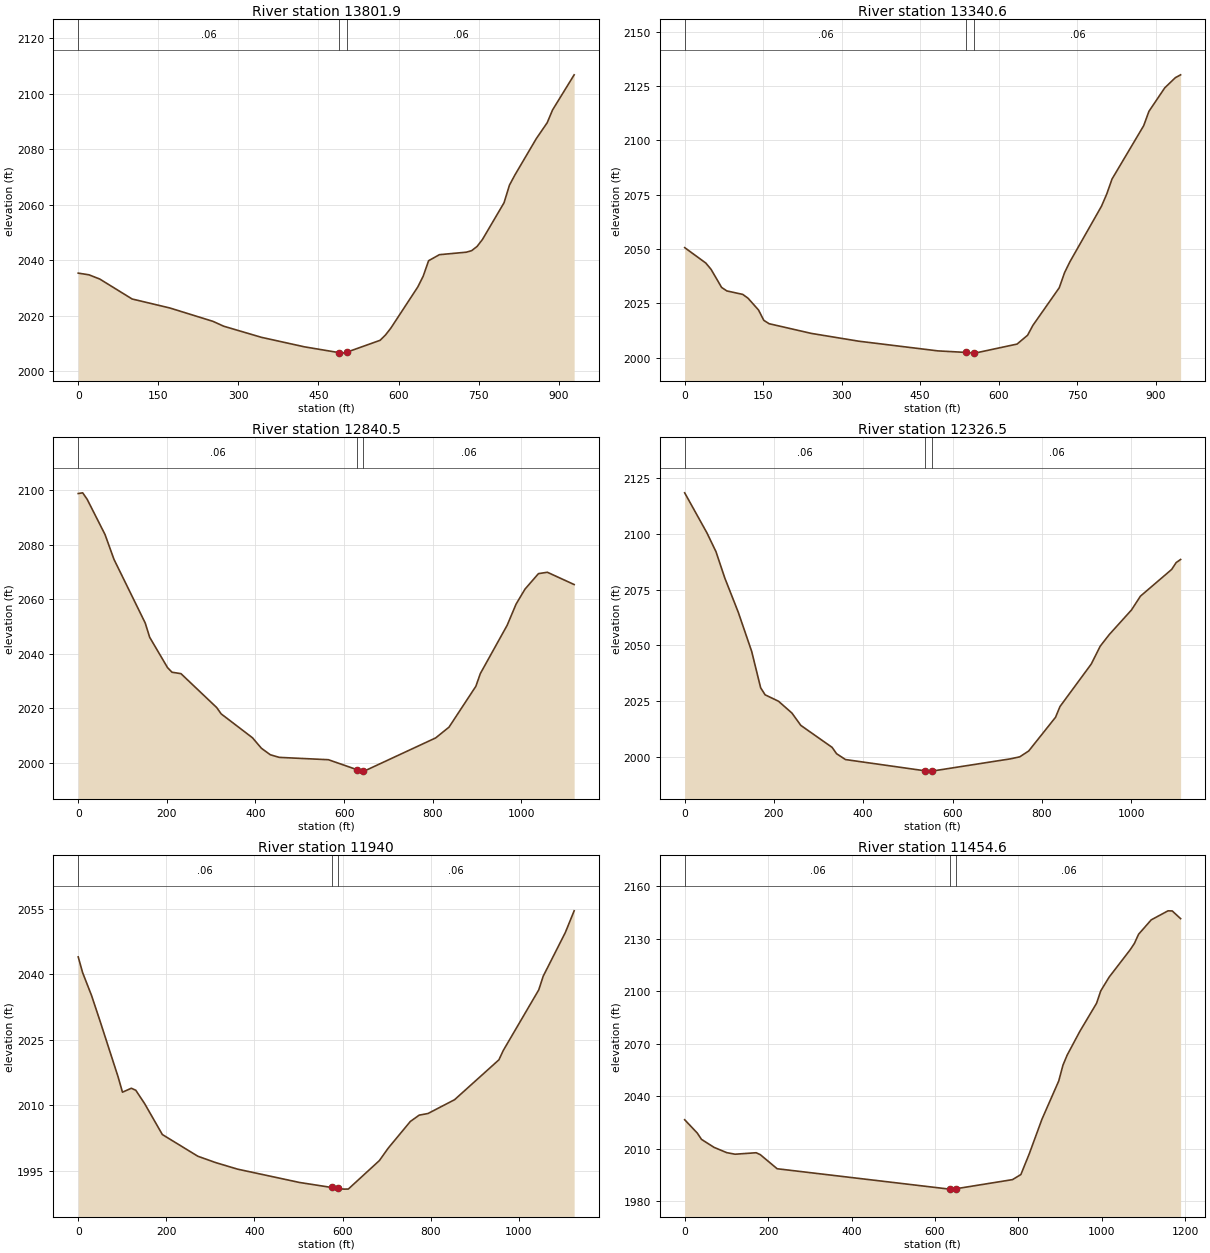
Type RM Length L Ch R = 1 ,13801.9 ,465.3,461.3,457.2
XS GIS Cut Line= 2
     2192423.665      325355.972       2193339.9      325203.266
#Sta/Elev= 30
       0 2035.37    20.2 2034.76    40.4 2033.23     101 2026.04   171.6  2022.8
   252.4 2017.98   272.6 2016.22   343.3 2012.21     424 2008.78   488.2 2006.71
   494.7 2006.52   503.2 2006.87   565.4 2011.14   575.5 2013.06   585.6 2015.55
   636.1  2030.4   646.2 2034.29   656.3 2039.85   676.5 2042.02   726.9 2042.92
     737 2043.48   747.1    2045   757.2 2047.52   797.6 2060.75   807.7 2067.09
   817.8 2070.72   858.2 2083.93   878.4  2089.6   888.5 2094.23   928.9 2106.88
#Mann= 3 , 0 , 0
       0     .06       0   488.2    .045       0   503.2     .06       0
Bank Sta=488.2,503.2
XS Rating Curve= 0 ,0
Exp/Cntr=0.3,0.1

Type RM Length L Ch R = 1 ,13340.6 ,500.1,500,499.9
XS GIS Cut Line= 2
     2192502.651      325890.442     2193397.823      325579.765
#Sta/Elev= 30
       0 2050.62    40.3 2043.55    50.4 2040.64    70.6  2032.3    80.6  2030.7
   110.9 2029.11     121 2027.36   141.1 2021.93   151.2 2017.17   161.3 2015.62
   241.9 2011.16   332.6 2007.57   483.9 2003.11   537.9  2002.4   552.9 2002.11
   554.4 2002.08   635.1 2006.25   655.2 2010.31   665.3 2014.84   715.7 2032.16
   725.8 2039.08   735.9 2044.05   796.4 2069.68   806.4 2075.26   816.5 2082.17
     877 2106.72   887.1 2113.35   917.3 2124.15   937.5 2128.82   947.6 2130.14
#Mann= 3 , 0 , 0
       0     .06       0   537.9    .045       0   552.9     .06       0
Bank Sta=537.9,552.9
XS Rating Curve= 0 ,0
Exp/Cntr=0.3,0.1

Type RM Length L Ch R = 1 ,12840.5 ,514.6,513.6,512.6
XS GIS Cut Line= 2
     2192534.245      326369.623     2193590.022       325998.39
#Sta/Elev= 30
       0 2098.71    10.1 2098.97    20.2  2096.6    60.5 2083.69    80.7 2074.59
   151.2 2051.27   161.3 2046.02   201.6  2034.9   211.7 2033.22   231.9  2032.7
   312.6 2020.26   322.6 2017.96   393.2 2009.21   413.4 2005.36   433.5 2002.98
   453.7 2002.02   564.6 2001.16   628.1 1997.57   643.1 1997.02   645.3 1996.98
   806.6 2009.15   836.8 2013.11   897.3 2028.07   907.4 2032.73   967.9 2050.42
   988.1  2058.2  1008.2 2063.68  1038.5 2069.35  1058.6 2069.86  1119.1 2065.36
#Mann= 3 , 0 , 0
       0     .06       0   628.1    .045       0   643.1     .06       0
Bank Sta=628.1,643.1
XS Rating Curve= 0 ,0
Exp/Cntr=0.3,0.1

Type RM Length L Ch R = 1 ,12326.5 ,386.4,386.6,386.6
XS GIS Cut Line= 2
     2192723.373      326844.397     2193754.137       326429.74
#Sta/Elev= 30
       0 2118.26      50  2100.3    70.1 2091.96    90.1 2080.06   120.1 2064.84
   150.1 2047.36   170.2 2031.09   180.2 2027.95   210.2 2025.08   240.2 2019.81
   260.2 2014.28   330.3 2004.45   340.3 2001.61   360.3    1999   539.3 1993.95
   550.5 1993.83   554.3 1993.85   730.7 1999.35   750.7 2000.23   770.7 2002.84
   830.8 2017.91   840.8 2022.72   910.8 2041.71   930.9  2049.7   950.9 2054.83
  1000.9 2065.88    1021 2072.06    1091 2084.02    1101 2087.07    1111 2088.46
#Mann= 3 , 0 , 0
       0     .06       0   539.3    .045       0   554.3     .06       0
Bank Sta=539.3,554.3
XS Rating Curve= 0 ,0
Exp/Cntr=0.3,0.1

Type RM Length L Ch R = 1 ,11940   ,479.7,485.4,485.4
XS GIS Cut Line= 2
     2192917.237      327177.939     2193940.146      326707.625
#Sta/Elev= 30
       0    2044      10  2040.4    30.2 2035.18    50.3 2029.08    90.5 2016.54
   100.5 2013.02   120.6 2013.92   130.7 2013.46   150.8  2010.4     191 2003.32
   271.4 1998.36   311.6 1996.91   361.9 1995.39   502.6 1992.34   575.3  1991.2
   590.3 1990.98   603.1 1990.82   613.2 1990.84   683.6 1997.35   703.7  2000.2
   753.9 2006.31     774 2007.76   794.1 2008.14   854.4  2011.3     955 2020.43
     965 2022.59  1045.4 2036.44  1055.5 2039.57  1105.8 2049.59  1125.8 2054.55
#Mann= 3 , 0 , 0
       0     .06       0   575.3    .045       0   590.3     .06       0
Bank Sta=575.3,590.3
XS Rating Curve= 0 ,0
Exp/Cntr=0.3,0.1

Type RM Length L Ch R = 1 ,11454.6 ,432,426.3,426.4
XS GIS Cut Line= 2
     2193013.425      327605.751     2194091.143      327103.752
#Sta/Elev= 30
       0 2026.57    30.2 2018.96    40.3 2015.35    70.5 2010.77   100.8 2007.76
   120.9 2006.86   171.3  2007.7   181.4 2006.59   221.7 1998.55   634.8  1986.9
   636.5  1986.9   651.5 1987.16   785.9 1992.33     806 1995.26   826.2 2007.18
   856.4 2026.82   896.7 2048.72   906.8 2057.75   916.9 2063.52   947.1 2077.02
   987.4 2093.17   997.5 2100.29  1017.6 2108.13    1068 2123.77  1078.1 2127.39
  1088.1 2132.61  1118.4 2140.85  1158.7 2146.02  1168.8 2145.95  1188.9 2141.55
#Mann= 3 , 0 , 0
       0     .06       0   636.5    .045       0   651.5     .06       0
Bank Sta=636.5,651.5
XS Rating Curve= 0 ,0
Exp/Cntr=0.3,0.1

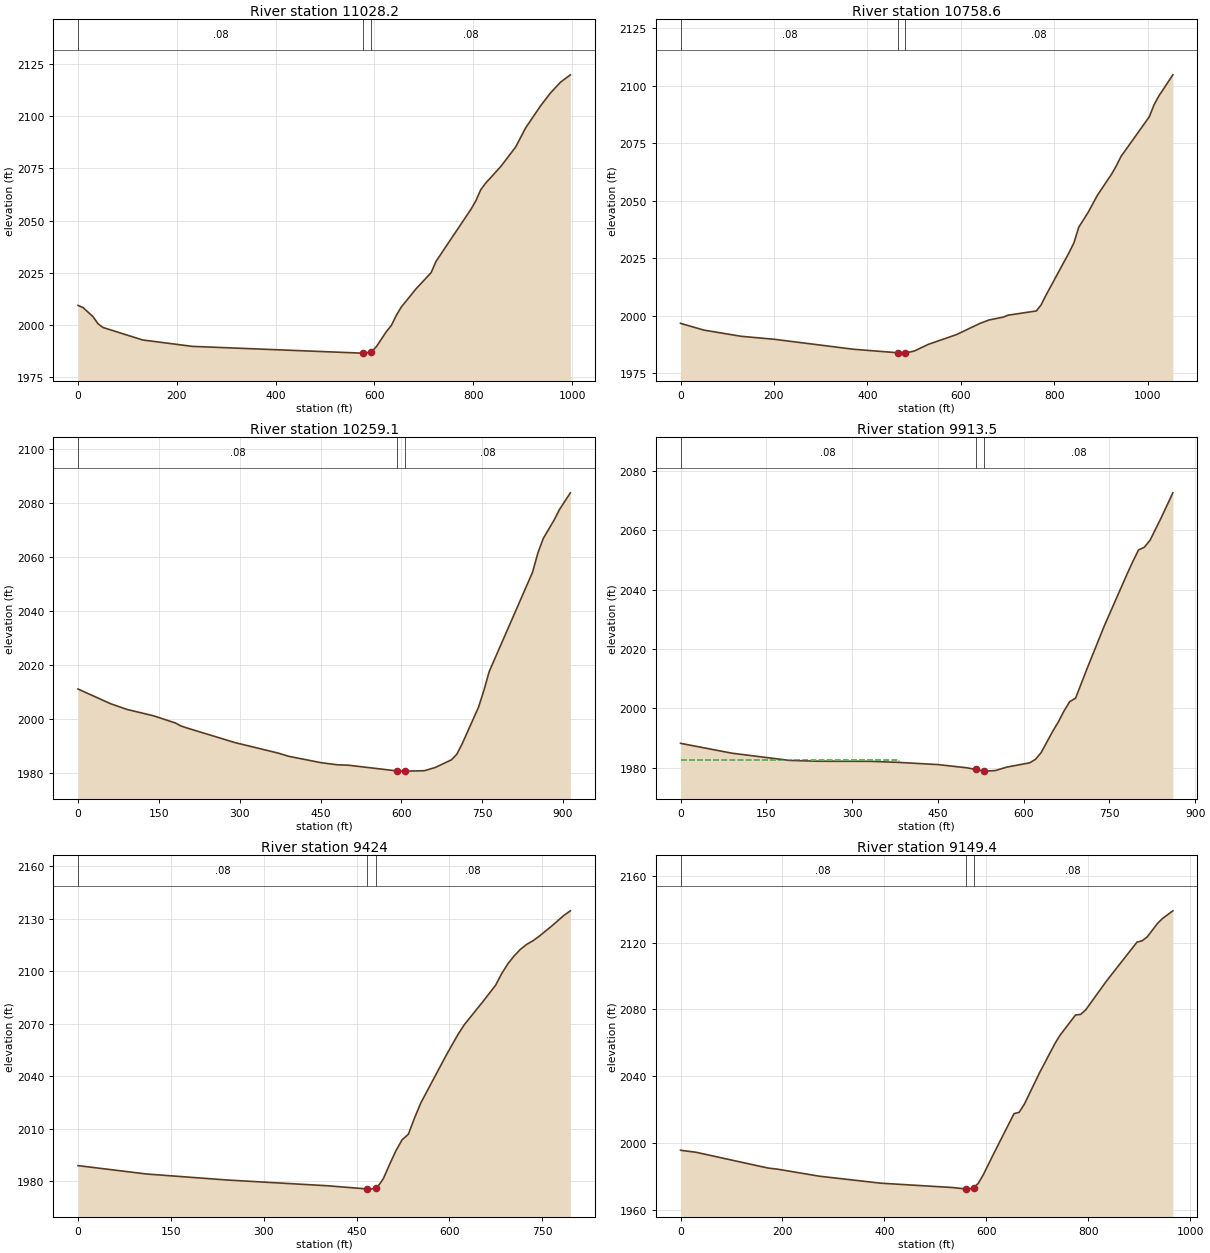
Type RM Length L Ch R = 1 ,11028.2 ,266.5,269.3,272.1
XS GIS Cut Line= 2
     2193292.509      327907.213     2194206.989      327510.968
#Sta/Elev= 30
       0 2009.33    10.1 2008.34    30.2 2003.98    40.3 2000.61    50.3 1998.79
   130.9 1992.78   231.5 1989.72   573.8 1986.48   577.3 1986.49   592.3    1987
     594  1987.1     604 1989.61   624.2 1996.81   634.2 1999.74   644.3 2004.59
   654.4 2008.59   684.6  2017.4   714.8 2025.08   724.8 2030.52   795.3  2055.4
   805.4 2059.56   815.4 2064.88   825.5 2068.06   855.7  2075.9   885.9 2085.28
     906 2094.42   936.2 2104.97   956.4 2111.19   976.5 2116.31   996.6 2119.87
#Mann= 3 , 0 , 0
       0     .08       0   577.3    .045       0   592.3     .08       0
Bank Sta=577.3,592.3
XS Rating Curve= 0 ,0
Exp/Cntr=0.3,0.1

Type RM Length L Ch R = 1 ,10758.6 ,493.1,499.6,500.8
XS GIS Cut Line= 3
     2193427.662      328065.624     2194063.059      327883.079
     2194427.271      328030.958
#Sta/Elev= 30
       0 1996.73    50.1 1993.79   130.2 1991.09   200.3 1989.81   370.6 1985.46
     466 1983.93   480.8 1983.78     481 1983.78   500.8 1984.72   530.9 1987.62
     591 1991.84   641.1 1996.71   661.1 1998.22   691.3 1999.45   701.4 2000.28
   761.9 2002.12     772 2004.73     782 2008.76   832.4 2027.65   842.5  2031.8
   852.6  2038.5   872.8 2044.98   892.9 2052.51   923.2 2061.66   933.2 2065.23
   943.3 2069.33  1003.8 2086.56  1013.9 2091.75    1024 2095.51  1054.2 2104.78
#Mann= 3 , 0 , 0
       0     .08       0     466    .045       0     481     .08       0
Bank Sta=466,481
XS Rating Curve= 0 ,0
Exp/Cntr=0.3,0.1

Type RM Length L Ch R = 1 ,10259.1 ,366.5,345.5,329.8
XS GIS Cut Line= 2
     2193587.389       328631.25     2194348.286      328125.741
#Sta/Elev= 30
       0 2011.13    60.2 2005.71    90.4  2003.6   140.5 2001.19   180.7 1998.54
   190.7 1997.48   200.8 1996.78   291.1 1991.29   371.4 1987.39   391.5 1986.18
   451.7 1983.81   481.8 1983.05   501.9  1982.9   591.5 1980.79   602.3 1980.71
   606.5 1980.71   642.5 1980.86   662.6 1982.04   692.7 1984.89   702.7 1986.92
   712.7 1990.82   742.9  2004.3   752.9 2010.49   762.9  2017.6   843.2 2054.34
   853.3 2061.57   863.3 2066.95   883.4 2073.77   893.4 2077.68   913.5 2083.83
#Mann= 3 , 0 , 0
       0     .08       0   591.5    .045       0   606.5     .08       0
Bank Sta=591.5,606.5
XS Rating Curve= 0 ,0
Exp/Cntr=0.3,0.1

Type RM Length L Ch R = 1 ,9913.5  ,487.5,489.5,491.5
XS GIS Cut Line= 2
     2193979.685      328984.053     2194487.827      328288.978
#Sta/Elev= 30
       0 1988.17    90.1 1984.84   190.2 1982.42   240.3 1982.13   330.4 1982.11
   380.4 1981.76   450.5    1981   500.6 1979.93   516.2 1979.38   530.6  1978.8
   531.2  1978.8   550.6 1978.99   570.7 1980.16   610.7 1981.61   620.7 1982.78
   630.7 1985.06   650.8  1992.2   660.8 1995.41   670.8 1999.13   680.8 2002.26
   690.8 2003.38   710.8 2013.29   740.9 2027.68   780.9 2045.24   790.9 2049.44
   800.9 2053.37     811 2054.29     821  2056.6     841 2064.38     861 2072.63
#Mann= 3 , 0 , 0
       0     .08       0   516.2    .045       0   531.2     .08       0
#XS Ineff= 2 , 0
          381.67 1982.62
Permanent Ineff=
       F       F
Bank Sta=516.2,531.2
XS Rating Curve= 0 ,0
Exp/Cntr=0.3,0.1

Type RM Length L Ch R = 1 ,9424    ,277.2,274.6,271.9
XS GIS Cut Line= 2
     2194358.817      329207.846     2194874.858      328602.289
#Sta/Elev= 30
       0 1988.93   110.8 1984.14   241.7  1980.7   402.8 1977.44   466.9 1975.63
   473.3 1975.51   481.9 1976.27   483.4  1976.4   493.5 1981.58   503.6 1989.71
   513.6 1997.37   523.7  2003.7   533.8 2006.84   543.8 2016.14   553.9 2024.71
   594.2 2051.44   614.3 2064.02   624.4 2069.49   654.6 2082.71   674.8 2091.93
   684.8 2098.67   694.9 2104.28     705 2108.76     715 2112.44   725.1 2115.27
   735.2 2117.31   745.3 2119.91   765.4  2125.7   785.5  2131.9   795.6  2134.4
#Mann= 3 , 0 , 0
       0     .08       0   466.9    .045       0   481.9     .08       0
Bank Sta=466.9,481.9
XS Rating Curve= 0 ,0
Exp/Cntr=0.3,0.1

Type RM Length L Ch R = 1 ,9149.4  ,310.7,318.5,326.4
XS GIS Cut Line= 3
     2194479.929      329415.842     2194759.012      329184.151
      2195095.14      328683.468
#Sta/Elev= 30
       0 1995.59    30.2  1994.4   171.3 1984.95   191.4  1984.2     272 1980.05
   392.9 1975.85   533.6 1973.25   560.1 1972.37   563.7 1972.29   573.8  1972.9
   575.1 1973.26   583.8 1975.64   593.9 1980.89     614 1993.33   654.2 2017.54
   664.2 2018.34   674.3 2023.11   704.4 2042.12   734.6 2059.65   744.6  2064.6
   774.8 2076.68   784.9 2077.05   794.9 2079.76   835.1 2096.84   895.4 2120.35
   905.5 2121.18   915.5 2123.51   935.6 2131.55   945.7 2134.58   965.8 2139.13
#Mann= 3 , 0 , 0
       0     .08       0   560.1    .045       0   575.1     .08       0
Bank Sta=560.1,575.1
XS Rating Curve= 0 ,0
Exp/Cntr=0.3,0.1

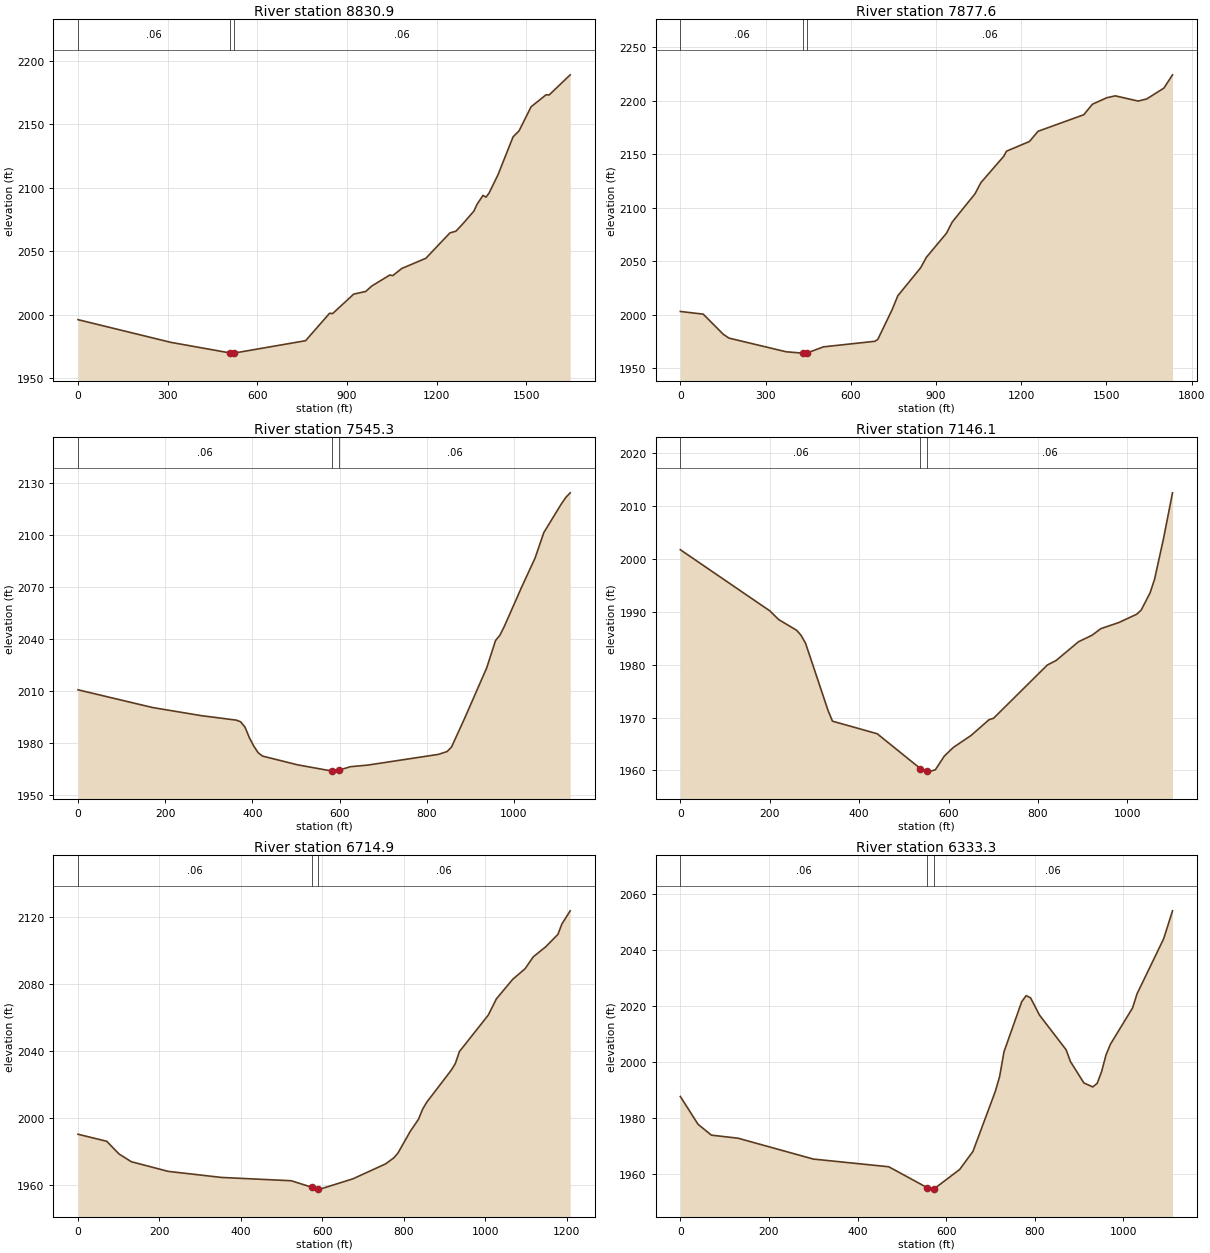
Type RM Length L Ch R = 1 ,8830.9  ,950.8,953.2,955.5
XS GIS Cut Line= 3
     2194669.495      329552.751     2195264.521      329110.431
     2195501.478      328236.321
#Sta/Elev= 30
       0 1995.95   310.6 1978.08     507 1969.82     521 1969.59     522 1969.61
   761.6 1979.39     842 2001.01   852.1 2000.76   922.6 2016.08   962.8 2018.16
   982.9 2022.43  1043.3 2031.09  1053.4 2030.67  1083.6 2036.28  1164.1  2044.3
  1244.6 2064.29  1264.7 2065.65  1284.8 2070.64  1325.1 2081.55  1335.1 2086.69
  1355.3 2093.86  1365.3 2092.45  1375.4 2095.58  1405.6 2110.13  1455.9 2139.95
    1476 2144.68  1516.3 2163.67  1566.6 2173.11  1576.6 2172.94  1647.1  2188.8
#Mann= 3 , 0 , 0
       0     .06       0     507    .045       0     522     .06       0
Bank Sta=507,522
XS Rating Curve= 0 ,0
Exp/Cntr=0.3,0.1

Type RM Length L Ch R = 1 ,7877.6  ,337.9,332.2,326
XS GIS Cut Line= 2
     2195011.766      330142.512     2196453.696      329181.957
#Sta/Elev= 30
       0 2003.09    80.6 2000.58   151.1 1981.78   171.2 1978.19   372.7 1965.42
   431.3 1964.17   446.3 1964.33   503.7 1970.03     685 1975.23     695 1976.97
   745.4 2004.66   765.6 2017.75   846.1 2043.95   866.3 2053.74   936.8 2076.11
     957 2086.56  1037.5 2113.06  1057.7  2123.3  1138.3 2147.98  1148.3  2152.8
  1228.9 2161.83  1259.1 2171.35  1420.3 2186.84  1450.5 2196.62  1500.9 2202.66
  1531.1 2204.47  1611.7  2199.6  1641.9 2201.58  1702.4 2211.72  1732.6  2224.1
#Mann= 3 , 0 , 0
       0     .06       0   431.3    .045       0   446.3     .06       0
Bank Sta=431.3,446.3
XS Rating Curve= 0 ,0
Exp/Cntr=0.3,0.1

Type RM Length L Ch R = 1 ,7545.3  ,400.1,399.1,398.1
XS GIS Cut Line= 2
     2195095.762      330531.783     2195911.657      329751.244
#Sta/Elev= 30
       0 2010.89   171.4 2000.66   282.3 1996.02   362.9 1993.43     373 1992.48
   383.1 1989.38   393.2 1983.26   403.3 1978.41   413.3 1974.64   423.4  1972.7
   504.1 1967.65   583.1 1964.06   584.7 1964.04   598.1 1964.58     625 1966.59
   665.4 1967.54   826.7 1973.69   846.8 1975.34   856.9 1977.95   887.2 1994.62
   937.6 2023.55   957.7 2039.21   967.8 2042.32   977.9 2047.39  1018.2 2070.32
  1048.5 2086.78  1068.6 2101.49    1109 2118.08    1119 2121.73  1129.1 2124.38
#Mann= 3 , 0 , 0
       0     .06       0   583.1    .045       0   598.1     .06       0
Bank Sta=583.1,598.1
XS Rating Curve= 0 ,0
Exp/Cntr=0.3,0.1

Type RM Length L Ch R = 1 ,7146.1  ,425,431,435.3
XS GIS Cut Line= 2
     2195349.823      330850.646     2196110.466      330055.107
#Sta/Elev= 30
       0 2001.74   200.1 1990.18   220.1 1988.52   260.2  1986.5   270.2 1985.53
   280.2 1984.02   330.2 1971.38   340.2 1969.32   440.3 1966.94     537 1960.34
     552 1959.95   560.3 1959.87   570.3 1960.13   590.4 1962.72   610.4 1964.34
   650.4 1966.63   690.4  1969.6   700.4 1969.86   820.5 1979.92   840.5  1980.8
   890.5 1984.34   920.6 1985.56   940.6 1986.82   980.6 1987.97  1020.6 1989.54
  1030.6 1990.32  1050.6  1993.6  1060.6 1996.16  1080.6 2003.86  1100.7  2012.5
#Mann= 3 , 0 , 0
       0     .06       0     537    .045       0     552     .06       0
Bank Sta=537,552
XS Rating Curve= 0 ,0
Exp/Cntr=0.3,0.1

Type RM Length L Ch R = 1 ,6714.9  ,367.3,381.8,397.9
XS GIS Cut Line= 2
     2195478.772      330974.478     2196591.483      330503.214
#Sta/Elev= 30
       0 1990.48    70.5 1986.27   100.7  1978.7   130.9 1974.08   221.5 1968.32
   352.4  1964.7   523.6 1962.73   574.7 1958.79   589.7 1957.87   594.1 1957.73
   674.7 1963.85   755.2 1972.79   775.4  1976.4   785.5 1979.26   815.7 1992.18
   835.8 1999.35   845.9 2005.33     856 2009.52   916.4  2028.7   926.4 2032.65
   936.5 2039.83    1007 2061.46  1027.1 2071.21  1067.4 2082.94  1097.6  2089.2
  1117.8 2096.34    1148 2102.24  1178.2  2109.7  1188.2    2116  1208.4 2123.76
#Mann= 3 , 0 , 0
       0     .06       0   574.7    .045       0   589.7     .06       0
Bank Sta=574.7,589.7
XS Rating Curve= 0 ,0
Exp/Cntr=0.3,0.1

Type RM Length L Ch R = 1 ,6333.3  ,344.9,347.6,350.3
XS GIS Cut Line= 2
     2195500.996      331080.971      2196611.12      331122.911
#Sta/Elev= 30
       0  1987.7      40 1977.76    70.1 1973.89   130.1  1972.8   300.2 1965.34
   470.4 1962.59   557.6 1955.09   570.5  1954.6   572.6 1954.69   630.5 1961.62
   660.5 1968.09   710.6 1989.37   720.6 1994.78   730.6 2003.71   770.6 2021.59
   780.6 2023.75   790.6 2022.94   810.7 2016.78   870.7  2004.4   880.7 2000.13
   910.8 1992.56   930.8 1991.12   940.8 1992.39   950.8 1996.56   960.8 2002.56
   970.8 2006.38  1020.8 2019.36  1030.8 2024.37  1090.9 2044.05  1110.9 2054.04
#Mann= 3 , 0 , 0
       0     .06       0   557.6    .045       0   572.6     .06       0
Bank Sta=557.6,572.6
XS Rating Curve= 0 ,0
Exp/Cntr=0.3,0.1