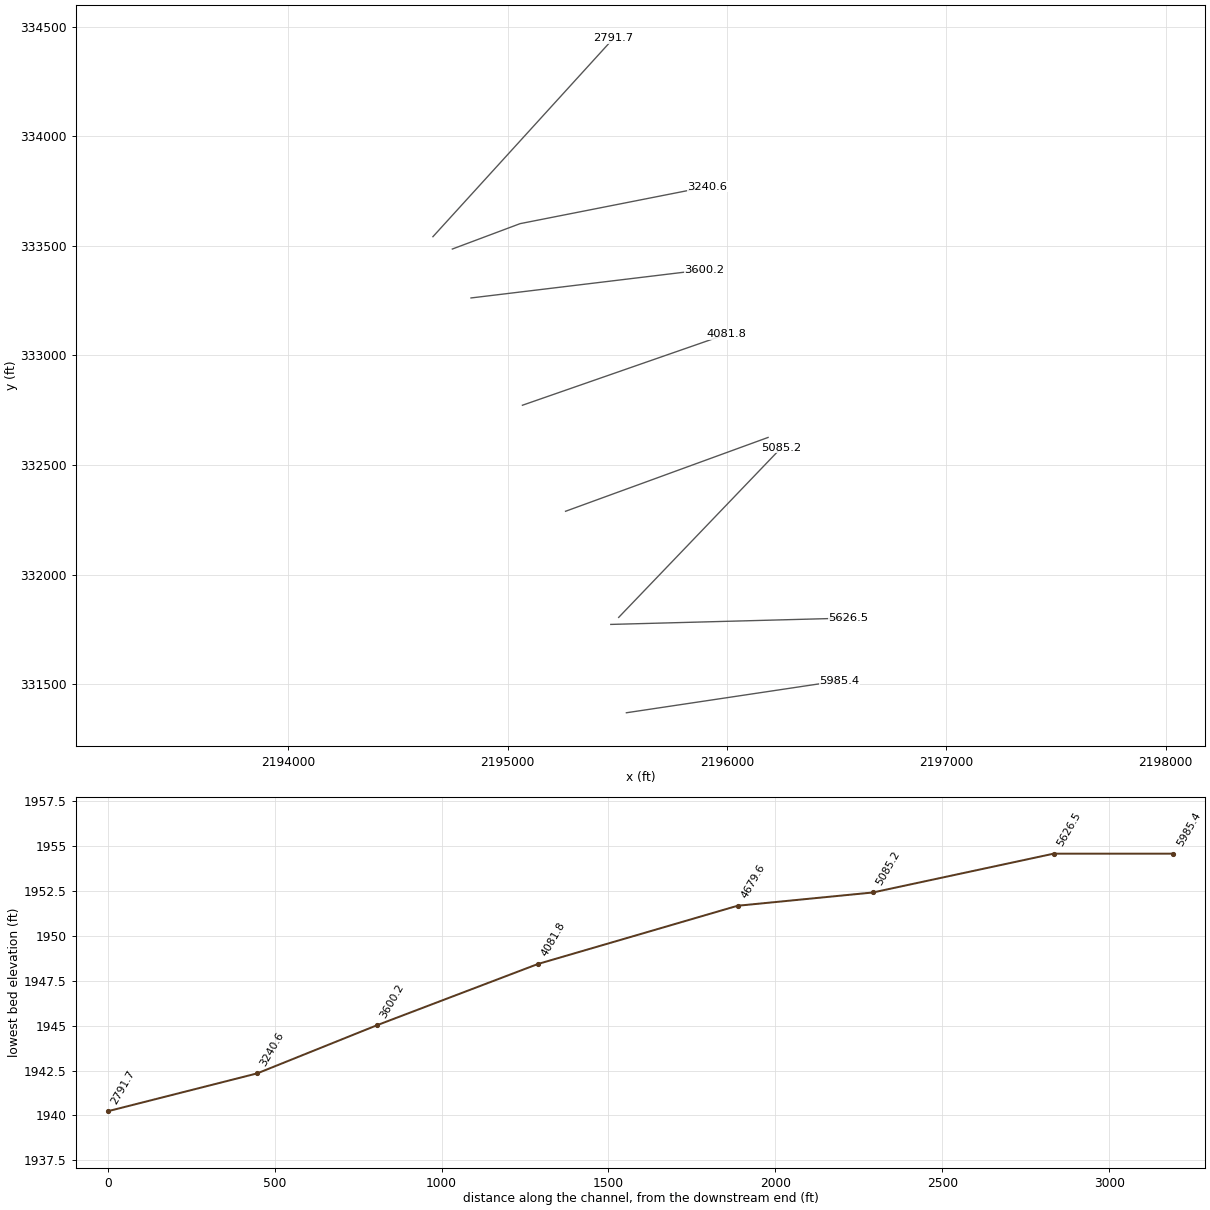
HEC-RAS study FlemRun.prj: FlemRun

--- FlemRun.g01 (geometry) --- (continued)

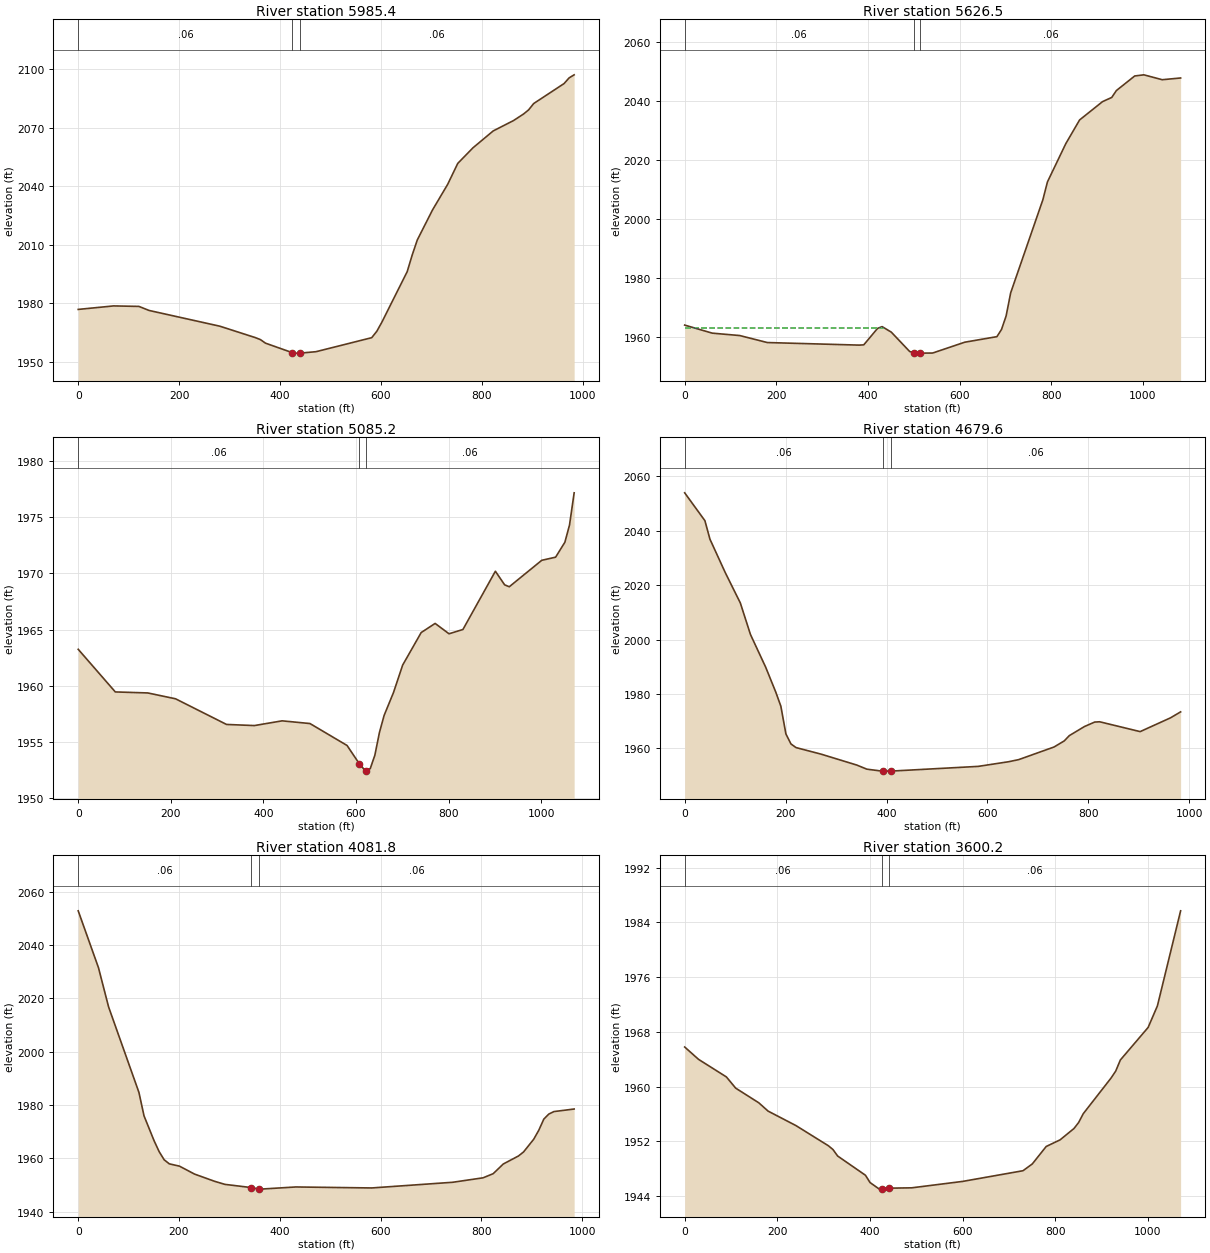
Type RM Length L Ch R = 1 ,5985.4  ,360.8,358.9,357
XS GIS Cut Line= 2
     2195540.971      331368.986     2196513.022      331514.853
#Sta/Elev= 30
       0 1976.95    70.2 1978.74   120.4 1978.49   140.4 1976.42   280.8 1968.35
     351 1962.52   361.1  1961.5   371.1 1959.68   424.6 1954.79   431.3 1954.57
   439.6 1954.57   471.4 1955.31   581.7 1962.48   591.8 1965.76   601.8 1970.41
     652 1996.28     662 2004.85     672 2012.49   702.1 2027.83   732.2 2040.97
   752.2  2051.7   782.3 2059.67   822.5 2068.34   862.6 2073.62   882.6 2076.99
   892.7 2079.12   902.7 2082.36   962.9 2092.58   972.9 2095.49   982.9 2097.06
#Mann= 3 , 0 , 0
       0     .06       0   424.6    .045       0   439.6     .06       0
Bank Sta=424.6,439.6
XS Rating Curve= 0 ,0
Exp/Cntr=0.3,0.1

Type RM Length L Ch R = 1 ,5626.5  ,523.6,541.4,559.1
XS GIS Cut Line= 2
     2195469.884      331772.252      2196551.99      331801.214
#Sta/Elev= 30
       0 1964.08    60.1 1961.35   120.3 1960.53   180.4 1958.16   380.9 1957.29
   390.9 1957.38     421 1962.96     431 1963.56     451 1961.69   491.1 1955.12
   499.5  1954.7   511.2 1954.57   514.5 1954.57   541.2  1954.6   611.4 1958.28
   681.6 1960.16   691.6 1962.62   701.6 1967.17   711.6 1975.04   781.8 2006.59
   791.8 2012.65   831.9 2025.64     862 2033.68   912.1  2039.9   932.2 2041.32
   942.2 2043.64   982.3  2048.6  1002.3 2048.99  1042.4 2047.33  1082.5 2047.92
#Mann= 3 , 0 , 0
       0     .06       0   499.5    .045       0   514.5     .06       0
#XS Ineff= 2 , 0
          435.73 1963.25
Permanent Ineff=
       F       F
Bank Sta=499.5,514.5
XS Rating Curve= 0 ,0
Exp/Cntr=0.3,0.1

Type RM Length L Ch R = 1 ,5085.2  ,415.2,405.4,396.1
XS GIS Cut Line= 2
     2195505.867      331804.285     2196246.578      332577.908
#Sta/Elev= 30
       0 1963.24    80.1 1959.45   150.2 1959.36   210.2 1958.84   320.3 1956.56
   380.4 1956.46   440.4 1956.88   500.5 1956.64   580.6 1954.69     607 1953.07
   620.6 1952.41     622 1952.44   630.6 1952.63   640.6 1953.82   650.6 1955.86
   660.6 1957.36   680.7 1959.38   700.7 1961.84   740.7 1964.73   770.8 1965.54
   800.8 1964.62   830.8    1965   900.9 1970.18   920.9 1968.97   930.9  1968.8
    1001 1971.15    1031 1971.43    1051 1972.76    1061 1974.29    1071 1977.15
#Mann= 3 , 0 , 0
       0     .06       0     607    .045       0     622     .06       0
Bank Sta=607,622
XS Rating Curve= 0 ,0
Exp/Cntr=0.3,0.1

Type RM Length L Ch R = 1 ,4679.6  ,598.8,597.7,596.2
XS GIS Cut Line= 2
     2195263.643      332288.732       2196186.9      332625.738
#Sta/Elev= 30
       0 2053.87    40.1 2043.64    50.1 2036.84    80.2 2024.66   110.3 2013.42
   130.4 2001.83   160.5 1989.85   180.5  1980.7   190.6 1975.51   200.6 1965.33
   210.6 1961.66   220.6 1960.32   270.8 1957.88     341  1953.9     361 1952.39
   391.1 1951.67   393.1 1951.67   408.1 1951.67   581.7 1953.41   641.9 1955.12
   661.9 1955.89   732.1 1960.54   752.2 1962.77   762.2  1964.7   792.3 1968.05
   812.4 1969.68   822.4 1969.79   902.6 1966.18   962.8 1971.24   982.8 1973.43
#Mann= 3 , 0 , 0
       0     .06       0   393.1    .045       0   408.1     .06       0
Bank Sta=393.1,408.1
XS Rating Curve= 0 ,0
Exp/Cntr=0.3,0.1

Type RM Length L Ch R = 1 ,4081.8  ,487.3,482.2,477.1
XS GIS Cut Line= 2
     2195067.056      332772.739     2195996.456      333096.581
#Sta/Elev= 30
       0  2052.8    40.2 2031.48    60.3 2016.76   120.5  1984.7   130.6 1975.91
   150.6 1966.57   160.7 1962.46   170.7 1959.41   180.8 1957.91   200.9 1957.05
     231 1954.06   271.2 1951.33   291.2 1950.21   343.6 1949.01   358.6 1948.46
   361.5 1948.43   431.8 1949.24   582.5 1948.87   743.2    1951   803.4 1952.67
   823.5 1954.22   843.6 1957.86   873.7 1960.86   883.8 1962.37   903.9 1967.13
   913.9 1970.46     924 1974.69     934 1976.59     944 1977.51   984.2 1978.47
#Mann= 3 , 0 , 0
       0     .06       0   343.6    .045       0   358.6     .06       0
Bank Sta=343.6,358.6
XS Rating Curve= 0 ,0
Exp/Cntr=0.3,0.1

Type RM Length L Ch R = 1 ,3600.2  ,355.8,358.7,361.6
XS GIS Cut Line= 2
     2194832.732      333262.451      2195895.53      333391.023
#Sta/Elev= 30
       0 1965.79      30 1963.98      90 1961.42   110.1 1959.78   160.1 1957.63
   180.1 1956.42   240.1 1954.31   310.2 1951.36   320.2  1950.8   330.2 1949.86
   390.2 1947.05   400.2 1945.98   420.2 1945.02   425.5 1945.04   440.5 1945.16
   490.2 1945.21   600.3 1946.15   730.4 1947.71   750.4  1948.7   780.4 1951.25
   810.4 1952.22   840.4 1953.88   850.4 1954.75   860.4 1956.04   920.5 1961.26
   930.5 1962.27   940.5 1963.89  1000.5 1968.65  1020.5  1971.8  1070.6 1985.69
#Mann= 3 , 0 , 0
       0     .06       0   425.5    .045       0   440.5     .06       0
Bank Sta=425.5,440.5
XS Rating Curve= 0 ,0
Exp/Cntr=0.3,0.1

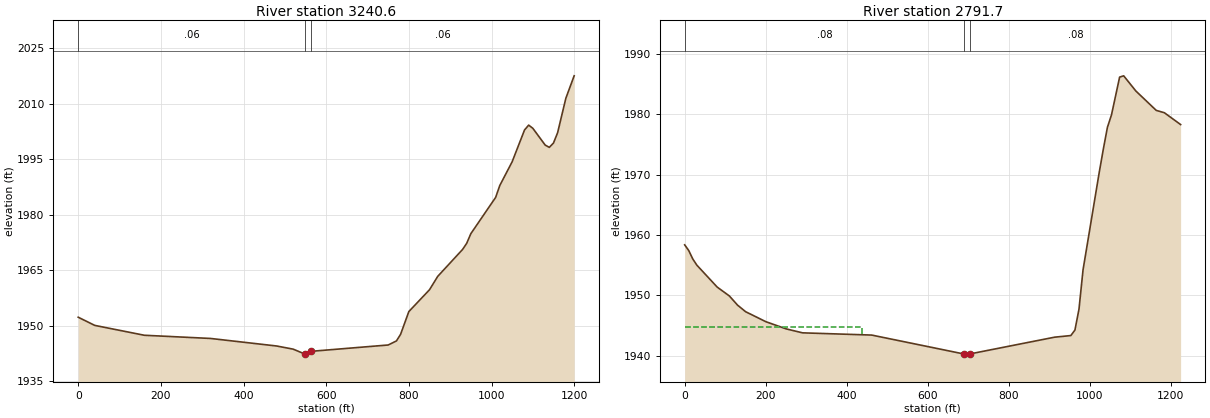
Type RM Length L Ch R = 1 ,3240.6  ,425.7,448,467.4
XS GIS Cut Line= 3
     2194747.603      333485.806     2195056.525      333601.651
     2195909.572      333770.155
#Sta/Elev= 30
       0 1952.32      40 1950.11     160 1947.44   319.9 1946.58   479.8 1944.54
   519.8 1943.69   548.6 1942.35   549.8 1942.34   563.6  1943.1   749.7 1944.81
   769.7 1945.91   779.7 1947.69   799.7 1953.85   849.6 1959.74   869.6 1963.37
   929.6 1970.64   939.6  1972.3   949.6  1974.9  1009.6 1984.72  1019.6 1987.92
  1049.5 1994.34  1079.5 2002.95  1089.5 2004.26  1099.5 2003.41  1129.5 1998.86
  1139.5 1998.25  1149.5 1999.42  1159.5 2002.21  1179.5 2011.55  1199.5 2017.59
#Mann= 3 , 0 , 0
       0     .06       0   548.6    .045       0   563.6     .06       0
Bank Sta=548.6,563.6
XS Rating Curve= 0 ,0
Exp/Cntr=0.3,0.1

Type RM Length L Ch R = 1 ,2791.7  ,2816.2,2791.4,2768.9
XS GIS Cut Line= 2
     2194659.082       333542.11     2195482.398      334447.675
#Sta/Elev= 30
       0 1958.35      10 1957.41    20.1    1956    30.1 1954.98    80.2 1951.35
   110.4 1949.87   130.4 1948.36   150.5 1947.26   200.6  1945.6   250.8 1944.41
   290.9 1943.76   461.5 1943.39   690.1 1940.24   692.2 1940.23   705.1 1940.28
   912.9 1943.04     953 1943.31   963.1 1944.22   973.1 1947.69   983.1 1954.21
  1023.2 1970.42  1033.3 1974.27  1043.3 1977.85  1053.3  1979.9  1073.4 1986.17
  1083.4 1986.38  1113.5 1983.86  1163.7 1980.65  1183.8 1980.26  1223.9  1978.3
#Mann= 3 , 0 , 0
       0     .08       0   690.1    .045       0   705.1     .08       0
#XS Ineff= 2 , 0
          438.52 1944.71
Permanent Ineff=
       F       F
Bank Sta=690.1,705.1
XS Rating Curve= 0 ,0
Exp/Cntr=0.3,0.1

Chan Stop Cuts=-1
Use User Specified Reach Order=0
Composite Channel Slope=5